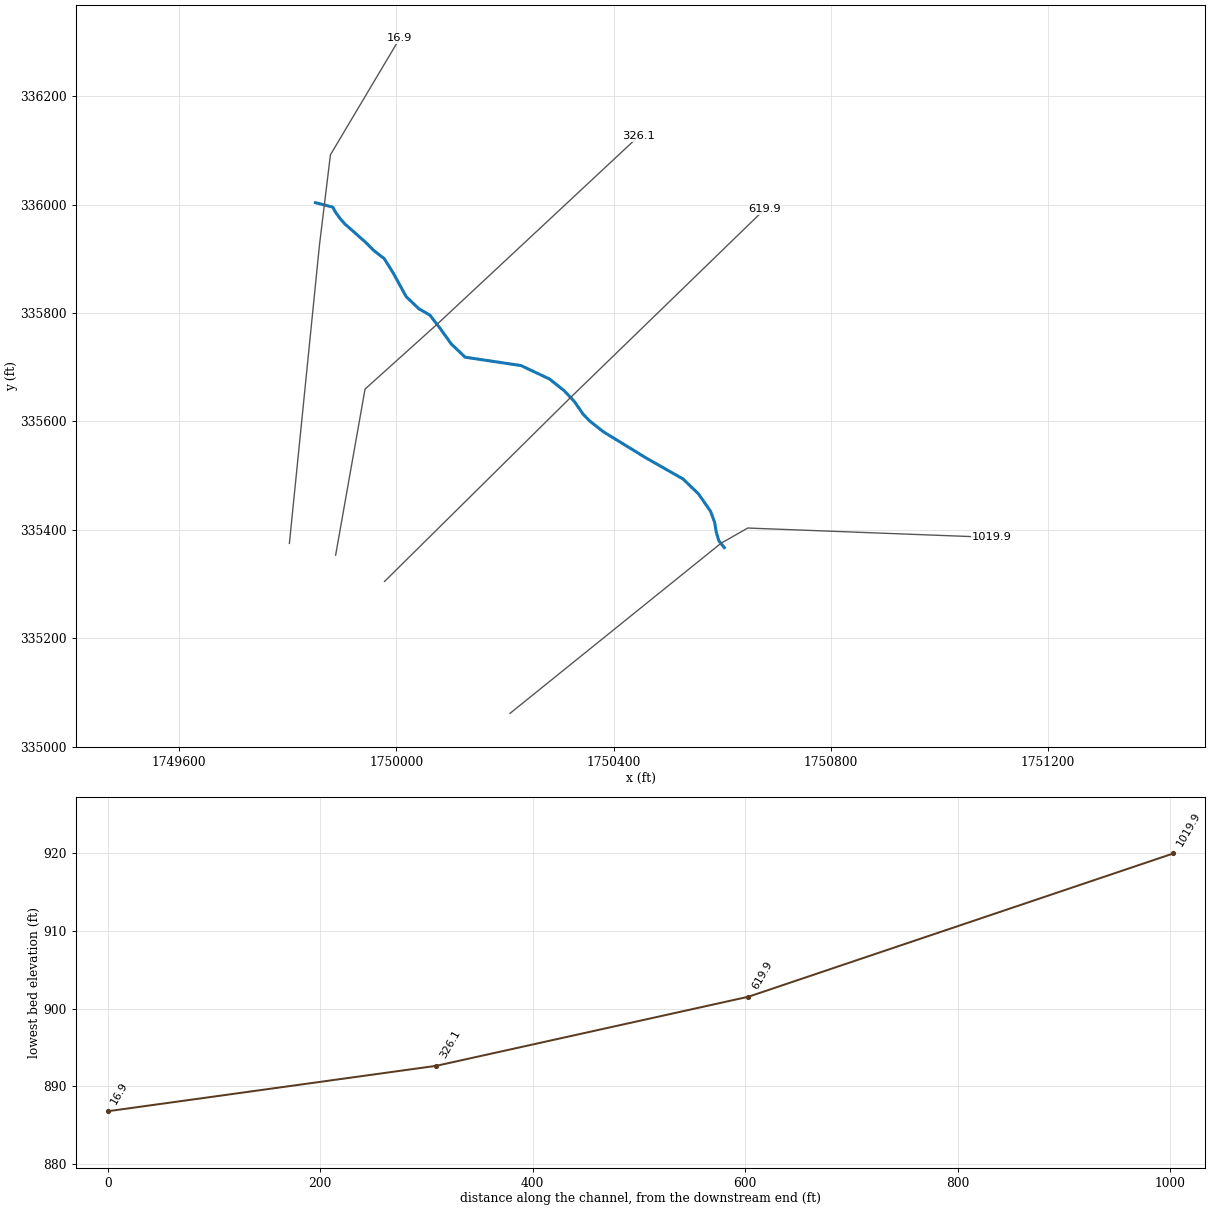
--- LaurlRnW.prj (project) ---

Proj Title=LaurlRnW
Current Plan=p01
Default Exp/Contr=0,0
English Units
Geom File=g01
Flow File=f01
Plan File=p01
BEGIN DESCRIPTION:
END DESCRIPTION:
DSS Export Rating Curves= 0
DSS Export Rating Curve Sorted= 0
DSS Export Volume Flow Curves= 0
DXF OffsetX= 0
DXF OffsetY= 0
DXF ScaleX= 0
DXF ScaleY= 0

--- LaurlRnW.p01 (plan) ---

Plan Title=Floodplain
Program Version=4.00
Geom File=g01
Flow File=f01
K Sum by GR=0
Std Step Tol=0.01
Critical Tol=0.01
Num of Std Step Trials=20
Max Error Tol=0.3
Flow Tol Ratio=0.001
Split Flow NTrial=30
Split Flow Tol=0.02
Split Flow Ratio=0.02
Log Output Level=0
Friction Slope Method=1
Unsteady Friction Slope Method=2
Unsteady Bridges Friction Slope Method=1
Global Log Level=0
CheckData=False
Run HTab=0
Run UNet=0
Run PostProcess=0
UNET Theta=0
UNET Theta Warmup=0
UNET ZTol=0
UNET ZSATol=0
UNET MxIter=0
UNET MaxInSteps=0
UNET DtIC=0
UNET DtMin=0
UNET MaxCRTS=0
UNET WFStab=0
UNET SFStab=0
UNET WFX=0
UNET SFX=0
UNET DSS MLevel=0
UNET DZMax Abort=0
UNET Convert EG Bridges=0
UNET Use Existing IB Tables=0
UNET Froude Limit=0
UNET Froude Power=0
Write IC File=0
Echo Input=False
Echo Output=False
Write Detailed=0

--- LaurlRnW.f01 (steady flow) ---

Flow Title=NFF Regression Equation
Program Version=4.00
Number of Profiles= 1
Profile Names=P100yr
River Rch & RM=LaurlRnW,Main            ,1019.9
618.1768
River Rch & RM=LaurlRnW,Main            ,619.9
855.2736
River Rch & RM=LaurlRnW,Main            ,326.1
859.0876
River Rch & RM=LaurlRnW,Main            ,16.9
  862.89
Boundary for River Rch & Prof#=LaurlRnW,Main            , 1
Up Type= 0
Dn Type= 3
Dn Slope=0.0331
DSS Import GetInterval= 0
DSS Import GetPeak= 0
DSS Import FillOption= 0

--- LaurlRnW.g01 (geometry) ---

Geom Title=USGS 3m DEM
Program Version=4.00

River Reach=LaurlRnW     ,Main
Reach XY= 30
     1750603.746      335367.299     1750593.653      335379.792
     1750588.575      335397.378     1750586.014      335413.728
     1750578.506      335434.134     1750556.267      335466.253
     1750527.815      335493.844     1750460.327      335532.273
     1750381.287      335580.792     1750356.052      335600.710
     1750343.966      335613.257     1750327.530      335637.055
     1750308.591      335657.043     1750282.086      335678.218
     1750229.646      335702.989     1750126.666      335718.466
     1750101.152      335742.917     1750079.890      335772.683
     1750061.818      335796.071     1750041.620      335807.765
     1750018.232      335830.090     1749993.780      335874.740
     1749977.834      335900.254     1749958.698      335915.137
     1749942.752      335931.083     1749905.544      335964.039
     1749897.039      335973.607     1749888.535      335985.301
     1749883.044      335995.210     1749851.239      336003.468

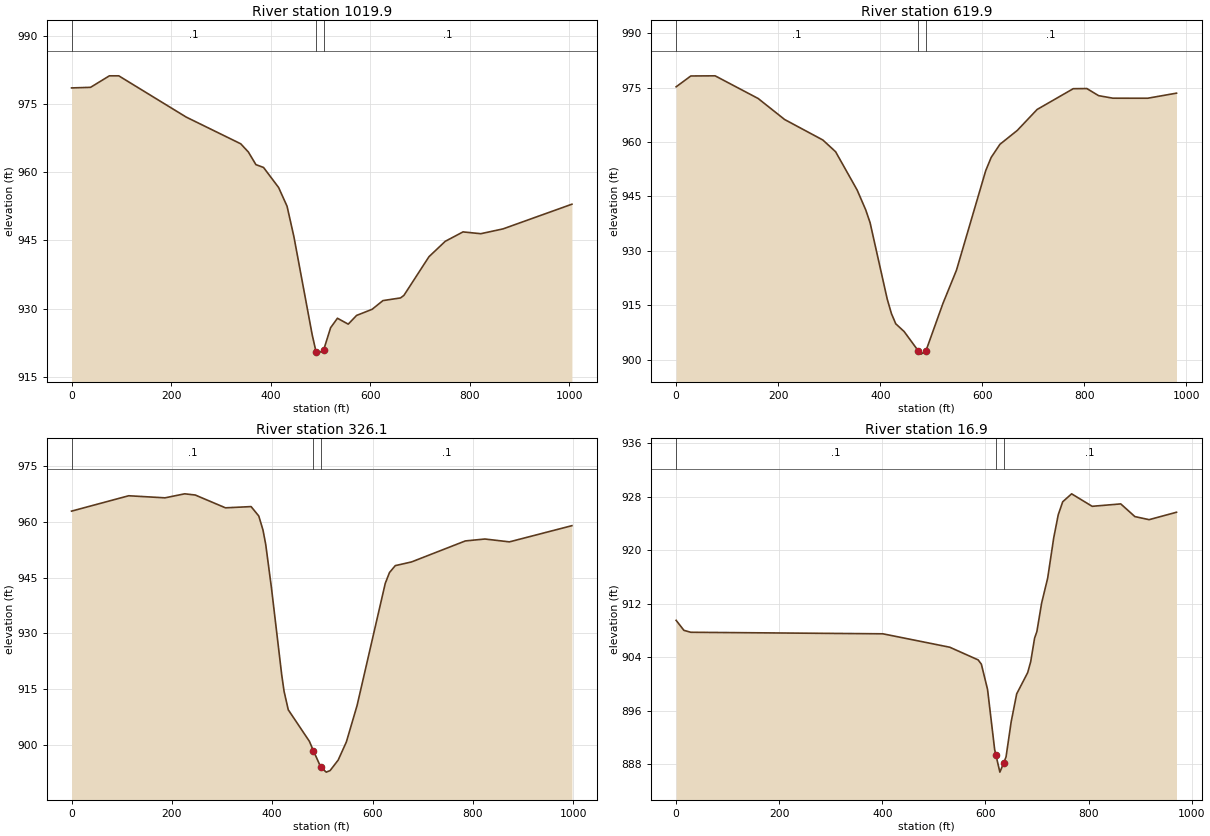
Type RM Length L Ch R = 1 ,1019.9,397.764,400,405.656
XS GIS Cut Line= 4
     1750209.304      335061.476     1750597.462      335375.078
     1750646.898      335403.336     1751096.144      335386.105
#Sta/Elev= 30
       0  978.52    38.2  978.65    76.0  981.18    94.9  981.18   230.5  972.10
   340.0  966.23   355.3  964.43   370.5  961.65   385.8  961.03   416.1  956.62
   433.1  952.49   446.8  945.82   483.7  924.17   491.5  920.40   492.6  919.98
   506.5  920.86   520.6  925.79   534.3  927.87   556.0  926.57   572.8  928.49
   603.9  929.83   625.7  931.75   661.1  932.34   667.9  932.90   718.3  941.41
   751.0  944.79   786.7  946.86   822.3  946.46   867.1  947.52  1005.5  952.95
#Mann= 3 , 0 , 0
       0     0.1       0   491.5   0.045       0   506.5     0.1       0
Bank Sta=   491.5,   506.5
Exp/Cntr=0.3,0.1

Type RM Length L Ch R = 1 ,619.9,295.232,293.819,293.026
XS GIS Cut Line= 3
     1749978.416      335304.812     1750320.828      335644.129
     1750678.136      335991.448
#Sta/Elev= 30
       0  975.24    28.8  978.23    76.4  978.27   160.7  972.02   212.6  966.22
   287.5  960.57   312.5  957.33   354.7  946.77   371.5  941.30   380.0  937.78
   413.7  916.65   421.9  912.69   430.3  909.89   446.7  907.76   474.6  902.40
   480.1  901.52   489.6  902.47   522.6  915.43   549.3  924.67   606.6  952.12
   617.4  955.79   634.5  959.39   668.5  963.22   707.3  968.99   778.1  974.72
   804.8  974.76   827.8  972.80   855.9  972.10   924.0  972.09   980.4  973.49
#Mann= 3 , 0 , 0
       0     0.1       0   474.6   0.045       0   489.6     0.1       0
Bank Sta=   474.6,   489.6
Exp/Cntr=0.3,0.1

Type RM Length L Ch R = 1 ,326.1,291.936,309.245,326.151
XS GIS Cut Line= 4
     1749888.374      335353.297     1749942.517      335659.651
     1750075.265      335779.319     1750446.091      336125.956
#Sta/Elev= 30
       0  962.92   113.9  967.06   186.2  966.50   225.5  967.58   246.5  967.26
   306.8  963.81   357.9  964.14   373.2  961.61   381.6  957.82   387.0  953.99
   398.4  942.33   418.9  918.85   423.6  914.40   432.0  909.41   474.1  900.92
   481.9  898.44   496.9  893.93   507.7  892.62   515.3  893.03   531.5  895.87
   547.8  900.75   569.1  910.54   625.3  943.45   633.7  946.36   645.3  948.24
   677.8  949.24   784.9  954.89   824.0  955.41   872.8  954.64   997.4  959.00
#Mann= 3 , 0 , 0
       0     0.1       0   481.9   0.045       0   496.9     0.1       0
Bank Sta=   481.9,   496.9
Exp/Cntr=0.3,0.1

Type RM Length L Ch R = 1 ,16.9,19.899,16.879,13.859
XS GIS Cut Line= 4
     1749803.253      335374.984     1749858.646      335925.550
     1749878.788      336091.726     1750006.358      336306.581
#Sta/Elev= 30
       0  909.51    15.1  908.01    28.4  907.72   401.1  907.49   530.8  905.48
   585.9  903.58   592.1  902.94   604.1  899.16   617.9  890.14   620.1  889.40
   628.0  886.77   635.1  888.08   640.0  889.06   649.9  894.30   660.6  898.49
   681.9  901.67   687.8  903.31   695.3  906.83   699.8  907.83   709.0  912.09
   720.7  915.83   732.5  921.88   741.2  925.32   749.9  927.27   767.2  928.46
   807.0  926.59   862.5  926.95   889.9  925.05   917.5  924.59   970.6  925.70
#Mann= 3 , 0 , 0
       0     0.1       0   620.1   0.045       0   635.1     0.1       0
Bank Sta=   620.1,   635.1
Exp/Cntr=0.3,0.1